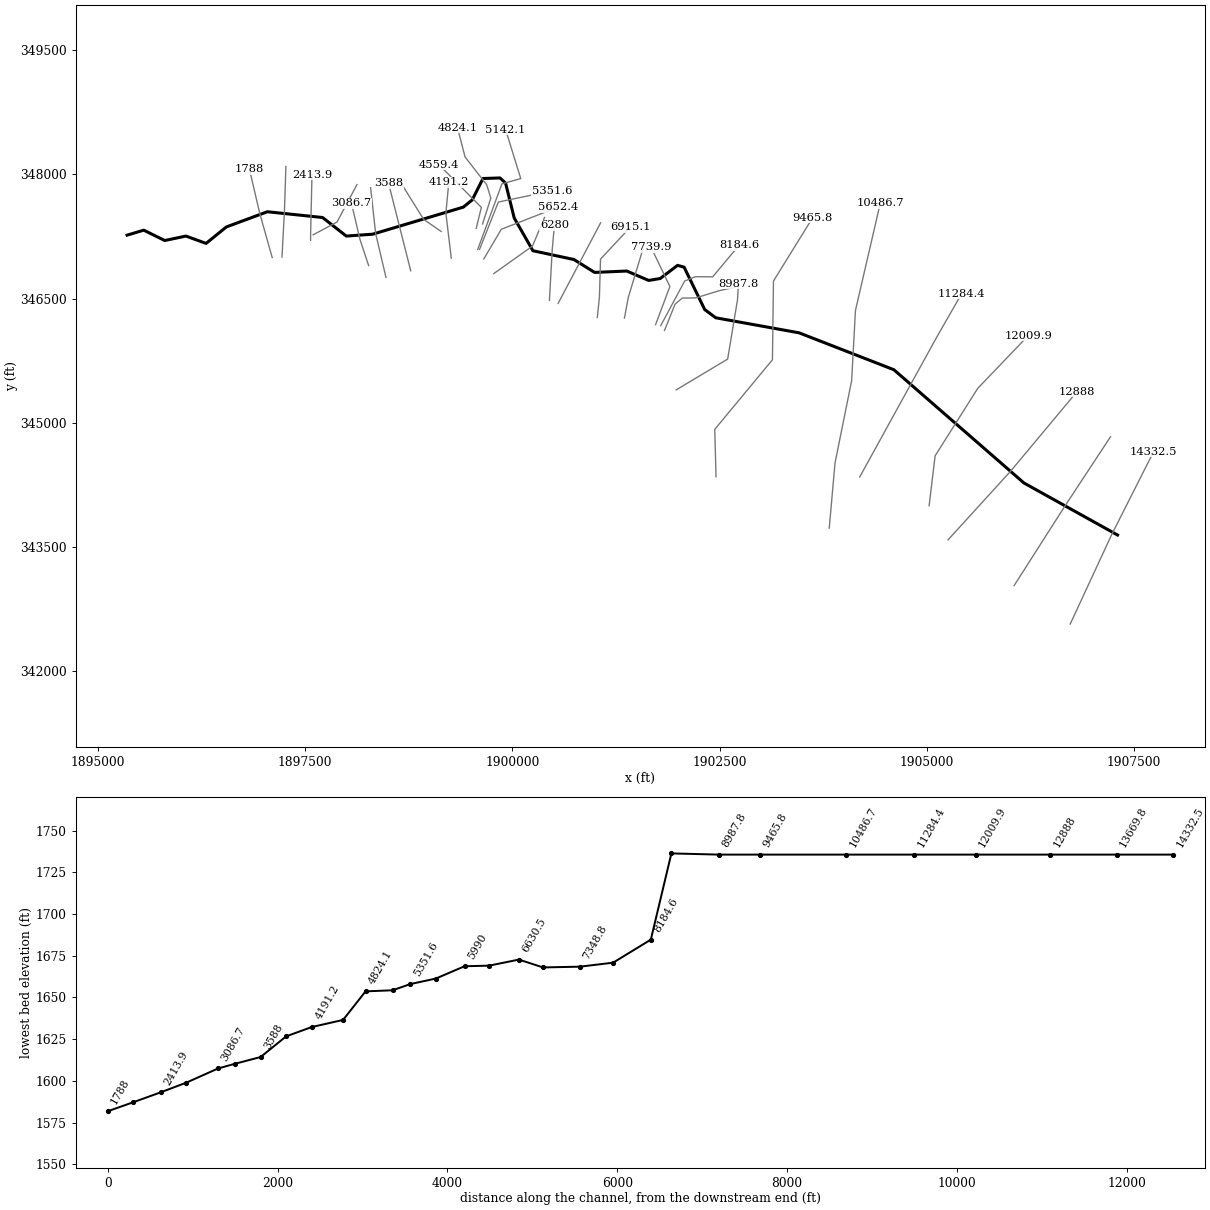
--- PlmOrchdCk.prj (project) ---

Proj Title=PlmOrchdCk
Current Plan=p01
Default Exp/Contr=0,0
English Units
Geom File=g01
Flow File=f01
Plan File=p01
BEGIN DESCRIPTION:
END DESCRIPTION:
DSS Export Rating Curves= 0
DSS Export Rating Curve Sorted= 0
DSS Export Volume Flow Curves= 0
DXF OffsetX= 0
DXF OffsetY= 0
DXF ScaleX= 0
DXF ScaleY= 0

--- PlmOrchdCk.p01 (plan) ---

Plan Title=Floodplain
Program Version=4.00
Geom File=g01
Flow File=f01
K Sum by GR=0
Std Step Tol=0.01
Critical Tol=0.01
Num of Std Step Trials=20
Max Error Tol=0.3
Flow Tol Ratio=0.001
Split Flow NTrial=30
Split Flow Tol=0.02
Split Flow Ratio=0.02
Log Output Level=0
Friction Slope Method=1
Unsteady Friction Slope Method=2
Unsteady Bridges Friction Slope Method=1
Global Log Level=0
CheckData=False
Run HTab=0
Run UNet=0
Run PostProcess=0
UNET Theta=0
UNET Theta Warmup=0
UNET ZTol=0
UNET ZSATol=0
UNET MxIter=0
UNET MaxInSteps=0
UNET DtIC=0
UNET DtMin=0
UNET MaxCRTS=0
UNET WFStab=0
UNET SFStab=0
UNET WFX=0
UNET SFX=0
UNET DSS MLevel=0
UNET DZMax Abort=0
UNET Convert EG Bridges=0
UNET Use Existing IB Tables=0
UNET Froude Limit=0
UNET Froude Power=0
Write IC File=0
Echo Input=False
Echo Output=False
Write Detailed=0

--- PlmOrchdCk.f01 (steady flow) ---

Flow Title=NFF Regression Equation
Program Version=4.00
Number of Profiles=1
Profile Names=P100yr
River Rch & RM=PlmOrchdCk,Main      ,14332.5
930.1523
River Rch & RM=PlmOrchdCk,Main      ,13669.8
944.7448
River Rch & RM=PlmOrchdCk,Main      ,11284.4
1046.799
River Rch & RM=PlmOrchdCk,Main      ,10486.7
1162.725
River Rch & RM=PlmOrchdCk,Main      ,9465.8
1420.282
River Rch & RM=PlmOrchdCk,Main      ,8987.8
1453.515
River Rch & RM=PlmOrchdCk,Main      ,6280
1582.965
River Rch & RM=PlmOrchdCk,Main      ,252.2
1750.889
Boundary for River Rch & Prof#=PlmOrchdCk,Main      ,1
Up Type=0
Dn Type=3
Dn Slope=0.031708

--- PlmOrchdCk.g01 (geometry) ---

Geom Title=USGS 3m DEM
Program Version=4.10

River Reach=PlmOrchdCk      ,Main
Reach XY= 30
     1907303.653      343646.283     1906173.445      344274.755
     1904604.001      345641.074     1903460.332      346086.229
     1902454.695       346267.81     1902321.384      346367.124
     1902072.751      346878.921     1901993.679      346900.418
     1901784.556      346741.769     1901645.166      346718.509
     1901380.042      346832.047     1900992.694      346815.125
     1900743.018      346971.032     1900248.098      347076.838
     1900022.404      347472.671     1899918.541       347892.13
       1899851.5      347955.102     1899645.683      347948.662
     1899515.459      347689.685      1899407.82       347602.88
      1898314.07      347276.491     1897996.362      347253.921
     1897709.904       347477.88     1897043.237      347547.324
     1896549.181      347364.111     1896304.063       347165.38
     1896060.598      347253.921      1895805.39      347200.102
     1895551.917      347325.102     1895351.115      347264.987

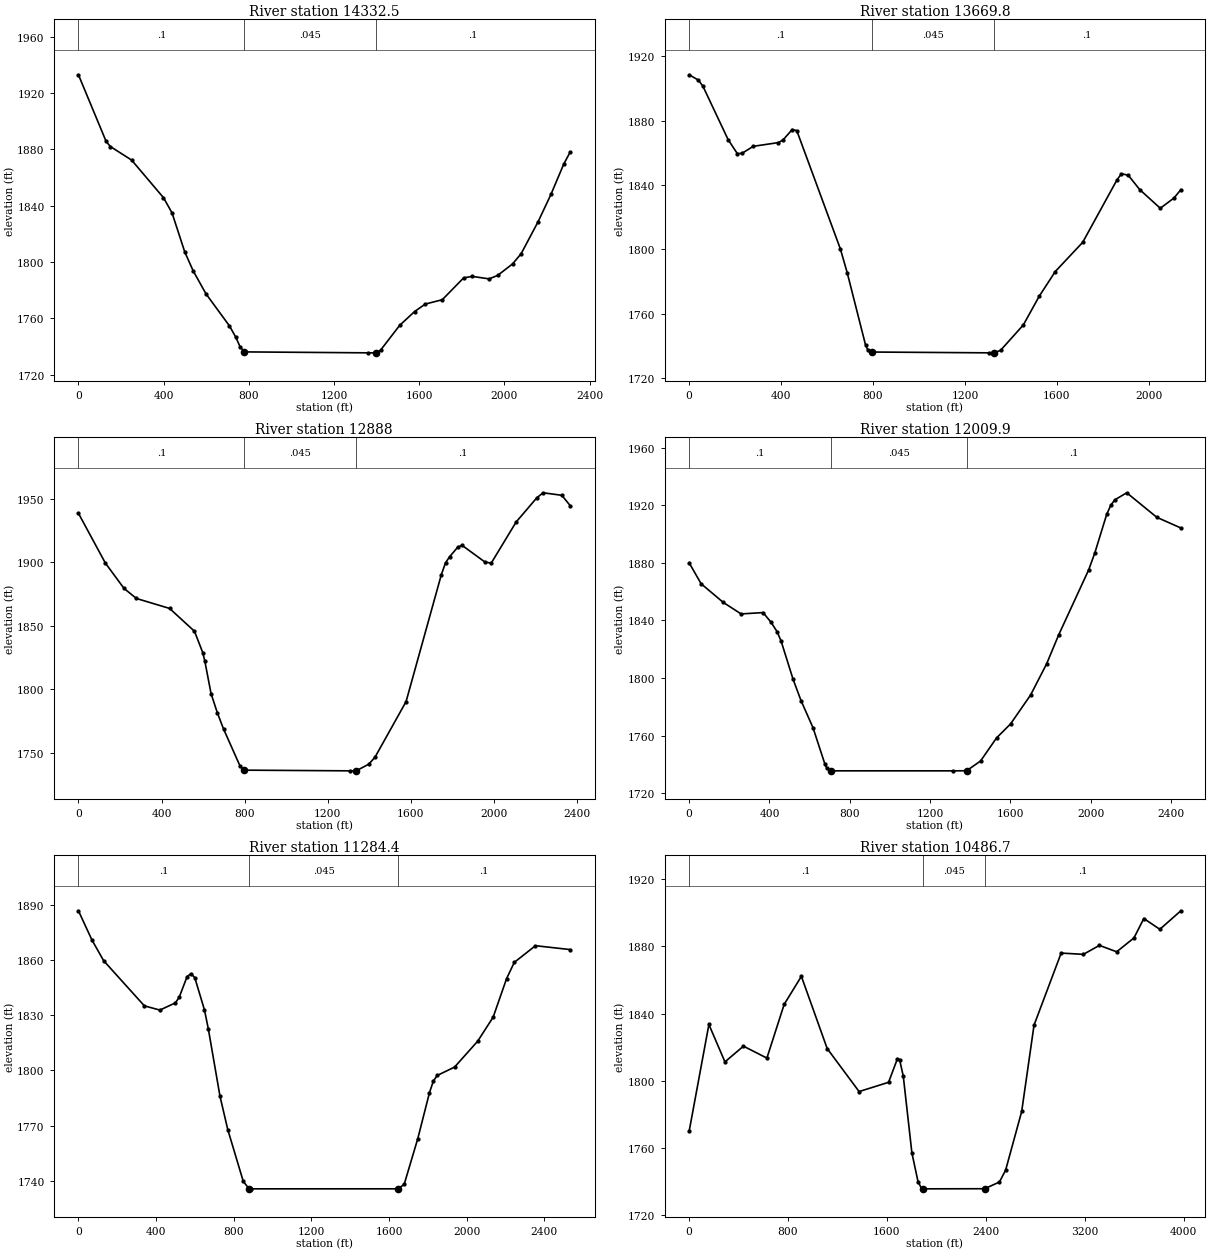
Type RM Length L Ch R = 1 ,14332.5 ,665.6,662.7,659.6
XS GIS Cut Line= 3
     1906732.547      342572.424     1907232.464      343650.487
     1907737.709      344650.512
#Sta/Elev= 30
       0 1932.88   129.8 1885.66   149.8 1881.98   249.6 1872.36   399.4 1845.67
   439.4  1834.9   499.3 1807.14   539.2 1793.61   599.2 1777.39     709 1754.72
     739 1746.65   758.9 1739.92   778.9 1736.25  1358.4 1735.58  1398.4  1735.6
  1418.4 1737.42  1508.4 1755.07  1578.5 1764.89  1628.5 1770.18  1708.5 1773.27
  1808.6 1788.74  1848.6 1789.83  1928.6 1788.05  1968.6 1790.54  2038.6 1798.69
  2078.7 1805.91  2158.7  1828.7  2218.7    1848  2278.7 1869.46  2308.8    1878
#Mann= 3 , 0 , 0
       0      .1       0   778.9    .045       0  1398.4      .1       0
Bank Sta=778.9,1398.4
XS Rating Curve= 0 ,0
Exp/Cntr=0.3,0.1

Type RM Length L Ch R = 1 ,13669.8 ,786.5,781.8,778.7
XS GIS Cut Line= 3
      1906054.91      343035.477     1906661.293      343984.824
     1907218.187      344831.215
#Sta/Elev= 30
       0 1908.48    39.9 1905.21    59.8 1901.42   169.5  1868.2   209.4 1859.53
   229.3 1859.56   279.1    1864   388.8 1866.32   408.7 1867.99   448.6 1874.45
   468.5 1873.72     658 1800.22   687.8 1785.42   767.6 1740.48   777.6 1737.32
   797.5 1736.08  1305.3 1735.58  1325.1 1735.58  1354.9 1737.09  1454.3 1752.93
  1523.8 1770.88  1593.3 1786.15  1712.5 1804.29  1861.5 1843.06  1881.4 1847.01
  1911.2 1845.94  1960.9 1837.06  2050.2 1825.47  2109.8 1831.86  2139.6 1837.03
#Mann= 3 , 0 , 0
       0      .1       0   797.5    .045       0  1325.1      .1       0
Bank Sta=797.5,1325.1
XS Rating Curve= 0 ,0
Exp/Cntr=0.3,0.1

Type RM Length L Ch R = 1 ,12888   ,873.2,878,881.7
XS GIS Cut Line= 3
     1905258.686       343588.88     1906011.113       344414.36
     1906811.605      345373.325
#Sta/Elev= 30
       0 1938.54   129.6 1899.32   219.4 1879.34   279.2 1871.41   438.8 1863.56
   558.5 1845.55   598.4 1828.69   608.3 1821.99   638.2 1796.43   668.2 1781.41
   698.1 1768.64   777.9 1739.27   797.8 1736.12  1306.8 1735.58  1336.8 1735.61
  1396.8  1740.8  1426.7  1746.2  1576.6 1790.14  1746.5 1890.29  1766.5 1899.55
  1786.5  1904.4  1826.5 1912.05  1846.4 1913.26  1956.4 1900.12  1986.4 1899.26
  2106.3  1931.7  2206.2 1950.84  2236.2 1954.72  2326.1 1952.73  2366.1 1944.65
#Mann= 3 , 0 , 0
       0      .1       0   797.8    .045       0  1336.8      .1       0
Bank Sta=797.8,1336.8
XS Rating Curve= 0 ,0
Exp/Cntr=0.3,0.1

Type RM Length L Ch R = 1 ,12009.9 ,724.1,725.7,727.4
XS GIS Cut Line= 4
     1905029.432      343999.742     1905101.995      344602.346
     1905616.998      345416.887     1906224.319      346050.963
#Sta/Elev= 30
       0 1880.05    59.7  1865.5   169.2 1852.62   258.7 1844.54   368.2 1845.48
     408 1838.75   437.8 1832.25   457.7 1825.82   517.4 1799.25   557.2 1784.34
   616.9  1765.5   676.5 1740.11   686.4 1737.25   706.3 1735.59  1312.3 1735.58
  1381.9 1735.64  1451.4 1742.43  1530.9 1758.46  1600.6 1768.15  1700.4 1788.23
  1780.2 1809.86    1840  1829.9  1989.7 1875.15  2019.6 1886.62  2079.5 1913.72
  2099.4 1919.88  2119.4 1923.74  2179.3 1928.68  2328.9 1911.65  2448.6 1904.24
#Mann= 3 , 0 , 0
       0      .1       0   706.3    .045       0  1381.9      .1       0
Bank Sta=706.3,1381.9
XS Rating Curve= 0 ,0
Exp/Cntr=0.3,0.1

Type RM Length L Ch R = 1 ,11284.4 ,785.3,797.8,810.3
XS GIS Cut Line= 3
     1904191.407      344345.575     1905111.865      346017.081
     1905422.448      346559.191
#Sta/Elev= 30
       0 1886.88    69.9 1870.91   129.9 1859.71   339.7 1835.14   419.6 1832.85
   499.5 1836.77   519.5 1839.93   559.5 1850.99   579.4  1852.7   599.4 1850.47
   649.4 1832.87   669.4 1822.46   729.3 1785.89   769.3 1767.82   849.2 1739.63
   879.2 1735.59   889.2 1735.58  1648.4 1735.59  1678.4 1738.14  1748.3 1762.95
  1808.3 1787.87  1828.3 1794.21  1848.2 1797.26  1937.9 1801.85  2056.9 1815.94
  2136.3 1828.97  2205.7 1849.98  2245.4 1858.81  2354.4 1867.88    2533 1865.77
#Mann= 3 , 0 , 0
       0      .1       0   879.2    .045       0  1648.4      .1       0
Bank Sta=879.2,1648.4
XS Rating Curve= 0 ,0
Exp/Cntr=0.3,0.1

Type RM Length L Ch R = 1 ,10486.7 ,1019.8,1020.8,1021.8
XS GIS Cut Line= 5
     1903824.354      343730.055     1903893.993      344515.747
     1904094.662      345508.893     1904140.584      346355.899
     1904439.874      347649.057
#Sta/Elev= 30
       0 1769.84   159.8 1833.49   289.6 1811.22   439.3 1820.58     629 1813.48
   768.8 1845.49     908 1862.18  1116.6 1819.18  1374.8 1793.54  1613.2 1799.04
  1682.8 1812.66  1702.6 1812.53  1732.4 1802.67    1802 1756.98  1851.9 1739.77
  1881.8 1735.58  1891.8 1735.58  2390.8 1735.65  2510.5 1739.66  2560.4 1746.76
  2690.2 1781.68    2790 1833.08  3009.5 1876.04  3189.2 1875.28  3318.9 1880.62
  3458.6 1876.81  3598.3 1885.05  3678.2 1896.62  3807.9  1890.2  3977.6 1901.24
#Mann= 3 , 0 , 0
       0      .1       0  1891.8    .045       0  2390.8      .1       0
Bank Sta=1891.8,2390.8
XS Rating Curve= 0 ,0
Exp/Cntr=0.3,0.1

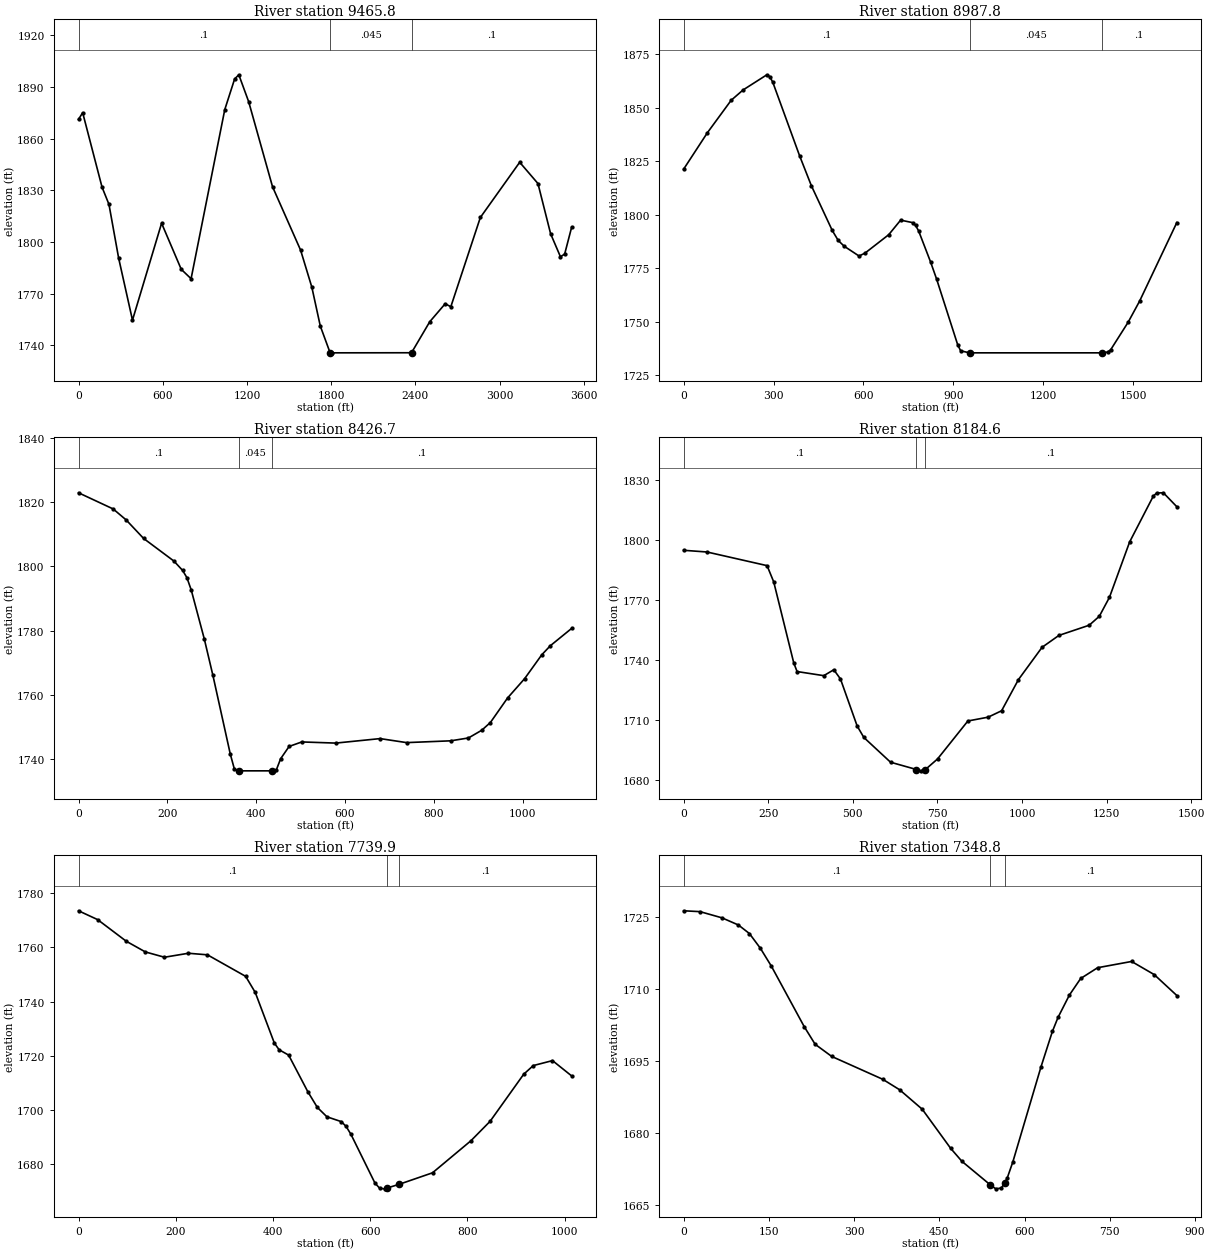
Type RM Length L Ch R = 1 ,9465.8  ,482.1,477.9,473.7
XS GIS Cut Line= 5
     1902457.951       344349.86      1902442.84       344921.52
     1903138.838      345761.054      1903151.08      346711.022
     1903625.496      347477.293
#Sta/Elev= 30
       0  1871.1    29.6 1875.01   167.6 1831.76   216.9 1821.78   285.9 1790.56
   384.5 1754.56   591.9 1810.82   731.9 1784.07     802  1778.6  1042.1 1876.81
  1112.1 1894.55  1142.1    1897  1212.2  1881.4  1382.2 1832.02  1582.3 1795.19
  1662.4 1773.67  1722.4 1751.19  1792.4 1735.63  1802.4 1735.58  2372.4 1735.63
  2502.4 1753.63  2612.4 1764.08  2652.5 1762.34  2862.8 1814.15  3143.2 1846.21
  3273.3 1833.86  3363.5  1804.7  3433.6 1791.34  3463.6 1792.94  3513.7 1808.65
#Mann= 3 , 0 , 0
       0      .1       0  1792.4    .045       0  2372.4      .1       0
Bank Sta=1792.4,2372.4
XS Rating Curve= 0 ,0
Exp/Cntr=0.3,0.1

Type RM Length L Ch R = 1 ,8987.8  ,592,561,530.3
XS GIS Cut Line= 4
      1901977.02      345397.485     1902598.457      345769.482
     1902716.714      346480.884     1902729.947      346681.272
#Sta/Elev= 30
       0 1821.41    79.4 1838.44   158.7 1853.59   198.4  1858.4   277.8 1865.49
   287.7 1864.58   297.6 1861.99   386.9  1827.7   426.6 1813.58   496.1 1792.74
   515.9  1788.1   535.8  1785.4   585.4 1780.82   605.2 1782.15   684.6 1790.78
   724.3 1797.58   764.3 1796.42   774.4 1795.09   784.4 1792.53   824.4 1777.99
   844.5    1770   914.6 1739.43   924.6 1736.52   954.6 1735.58  1395.4 1735.58
  1415.4 1735.93  1425.4 1737.01  1483.7 1749.87  1521.9 1759.71  1646.3 1796.45
#Mann= 3 , 0 , 0
       0      .1       0   954.6    .045       0  1395.4      .1       0
Bank Sta=954.6,1395.4
XS Rating Curve= 0 ,0
Exp/Cntr=0.3,0.1

Type RM Length L Ch R = 1 ,8426.7  ,239.5,242.1,244.5
XS GIS Cut Line= 6
      1901836.56      346115.221     1901963.837      346432.404
     1902050.471      346505.593     1902212.729      346507.865
     1902500.207       346595.55     1902688.364      346637.319
#Sta/Elev= 30
       0 1822.89    78.1 1817.85   107.4 1814.42   146.5 1808.68   214.8 1801.63
   234.4 1798.72   244.1 1796.46   253.9  1792.6   283.2 1777.41   302.7    1766
   341.8 1741.53   351.2 1736.76   360.7  1736.3   436.3  1736.3   445.7 1736.66
   455.2 1740.07   474.3  1743.9   502.9  1745.3   579.3 1744.94   679.2 1746.34
   738.9 1745.09   838.4 1745.65   878.2 1746.54   908.1 1748.94   927.6 1751.35
   966.2 1758.98  1004.7 1765.01  1043.3 1772.44  1062.6 1775.26  1110.7 1780.67
#Mann= 3 , 0 , 0
       0      .1       0   360.7    .045       0   436.3      .1       0
Bank Sta=360.7,436.3
XS Rating Curve= 0 ,0
Exp/Cntr=0.3,0.1

Type RM Length L Ch R = 1 ,8184.6  ,398.8,444.2,489.7
XS GIS Cut Line= 5
     1901790.573       346173.03     1902079.923      346711.483
     1902208.768      346763.417     1902418.023      346762.088
     1902737.244      347144.138
#Sta/Elev= 30
       0 1794.74      69 1793.89   246.5 1787.08   266.2 1778.94   325.4  1738.5
   335.2 1734.21   414.1 1732.16   443.7 1735.11   463.4  1730.5   512.7 1707.03
   532.4 1701.32   611.3 1688.96     688 1685.31   700.6 1684.65     713 1685.11
   750.2 1690.58   839.9 1709.54   899.7 1711.44   939.5 1714.64   989.3  1730.2
    1059  1746.3  1108.8 1752.25  1198.4 1757.34  1228.3 1761.81  1258.2 1771.26
  1317.9 1798.93  1387.6 1821.73  1397.6 1823.34  1417.5 1823.45  1457.3 1816.48
#Mann= 3 , 0 , 0
       0      .1       0     688    .045       0     713      .1       0
Bank Sta=688,713
XS Rating Curve= 0 ,0
Exp/Cntr=0.3,0.1

Type RM Length L Ch R = 1 ,7739.9  ,411.6,391.3,371.1
XS GIS Cut Line= 3
     1901728.617      346184.923     1901901.249      346644.778
     1901674.929      347116.477
#Sta/Elev= 30
       0 1773.55    39.3 1770.29    98.2  1762.3   137.5 1758.35   176.8 1756.39
     226 1757.86   265.2 1757.28   343.8 1749.33   363.5 1743.39   402.8 1724.69
   412.6 1722.22   432.2 1720.24   471.5 1706.77   491.2 1700.93   510.9 1697.46
   540.6 1695.67   550.4  1693.9   560.3    1691   609.6 1673.02   619.5 1671.04
   629.4 1670.85   634.9 1671.16   659.9 1672.55   728.1 1676.77   807.1 1688.61
   846.6  1695.8   915.7 1713.19   935.4 1716.38   974.9 1718.21  1014.4 1712.54
#Mann= 3 , 0 , 0
       0      .1       0   634.9    .045       0   659.9      .1       0
Bank Sta=634.9,659.9
XS Rating Curve= 0 ,0
Exp/Cntr=0.3,0.1

Type RM Length L Ch R = 1 ,7348.8  ,426.5,433.7,441
XS GIS Cut Line= 3
     1901353.088      346264.852      1901398.58      346511.368
     1901577.254      347102.183
#Sta/Elev= 30
       0 1726.28    28.9  1726.1    67.5 1724.81    96.4 1723.32   115.7 1721.55
     135 1718.49   154.3 1714.78   212.1  1702.2   231.4 1698.52   260.6 1695.99
   350.2 1691.25   380.1 1689.06   419.9 1685.01   469.7 1676.91   489.6 1674.19
   539.7 1669.28   549.3 1668.46   559.3 1668.63   564.7 1669.72   569.2 1670.63
   579.2 1674.02     629 1693.88   648.9 1701.19   658.8  1704.1   678.8 1708.75
   698.7  1712.2   728.5 1714.44   788.3 1715.74   828.1 1713.01   867.9 1708.66
#Mann= 3 , 0 , 0
       0      .1       0   539.7    .045       0   564.7      .1       0
Bank Sta=539.7,564.7
XS Rating Curve= 0 ,0
Exp/Cntr=0.3,0.1

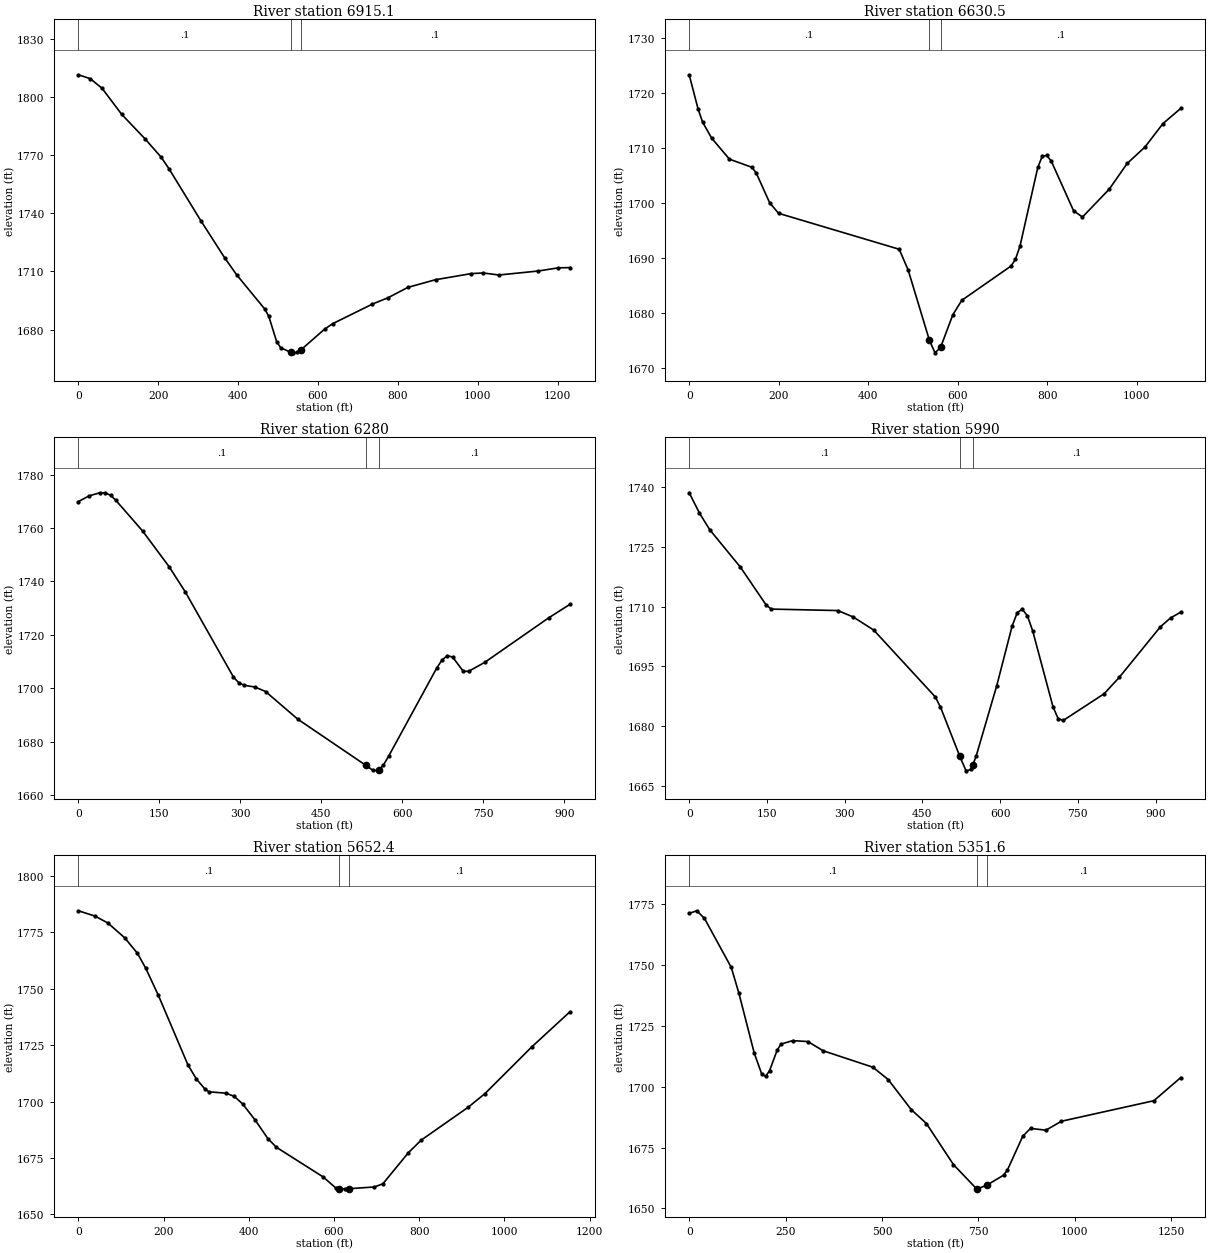
Type RM Length L Ch R = 1 ,6915.1  ,296.7,284.1,271.6
XS GIS Cut Line= 4
      1901025.61       346270.98     1901050.761      346516.132
     1901064.152      346975.877     1901422.403      347359.473
#Sta/Elev= 30
       0 1811.43    29.6 1809.42    59.2 1804.45   108.4    1791   167.6  1778.2
     207 1768.95   226.7 1762.97   306.4 1736.19   366.4 1716.95   396.4  1708.2
   466.4 1690.65   476.4 1686.99   496.4 1673.79   506.4 1670.66   531.2 1668.28
   536.4    1668   546.4 1668.24   556.2 1669.36   616.4 1680.21   636.4 1683.01
   736.1 1693.14   775.7 1696.46   825.2 1701.78   894.5 1705.73   983.7 1708.87
  1013.4  1709.2    1053 1708.15    1152 1710.22  1201.5 1711.84  1231.2 1711.97
#Mann= 3 , 0 , 0
       0      .1       0   531.2    .045       0   556.2      .1       0
Bank Sta=531.2,556.2
XS Rating Curve= 0 ,0
Exp/Cntr=0.3,0.1

Type RM Length L Ch R = 1 ,6630.5  ,338.7,350.5,362.3
XS GIS Cut Line= 2
     1900552.741      346441.628     1901064.983      347413.437
#Sta/Elev= 30
       0 1723.28      20 1717.01      30 1714.67    49.9 1711.78    89.9 1707.93
   139.8 1706.46   149.8 1705.42   179.8    1700   199.7 1698.08   469.4 1691.54
   489.4 1687.74   536.8 1674.98   549.3  1672.7   561.8  1673.7   589.2 1679.64
   609.2 1682.26     719 1688.48     729  1689.7     739 1692.06     779 1706.44
     789 1708.47   798.9  1708.6   808.9 1707.61   858.9 1698.55   878.8  1697.4
   938.8 1702.49   978.7 1707.15  1018.6 1710.15  1058.6  1714.4  1098.6 1717.18
#Mann= 3 , 0 , 0
       0      .1       0   536.8    .045       0   561.8      .1       0
Bank Sta=536.8,561.8
XS Rating Curve= 0 ,0
Exp/Cntr=0.3,0.1

Type RM Length L Ch R = 1 ,6280    ,314.8,290,265.1
XS GIS Cut Line= 3
     1900447.372      346477.228     1900481.387      347090.271
     1900507.593      347385.679
#Sta/Elev= 30
       0 1769.91    19.8 1772.04    39.6 1773.19    49.5 1773.14    59.4 1772.28
    69.3 1770.37   118.8 1758.89   168.4 1745.38   198.1 1736.02   287.2 1704.16
   297.1 1702.05     307 1701.11   326.8 1700.47   346.6 1698.78     406 1688.46
   531.8 1671.21   544.7 1669.37   554.6 1669.08   556.8 1669.54   564.5 1671.13
   574.4 1674.52   663.4 1707.49   673.3 1710.54   683.2  1712.2   693.1 1711.68
   712.8 1706.33   722.7 1706.34   752.4 1709.68     871 1726.37   910.6 1731.44
#Mann= 3 , 0 , 0
       0      .1       0   531.8    .045       0   556.8      .1       0
Bank Sta=531.8,556.8
XS Rating Curve= 0 ,0
Exp/Cntr=0.3,0.1

Type RM Length L Ch R = 1 ,5990    ,344.3,337.5,330.7
XS GIS Cut Line= 3
     1899775.525       346800.65     1900243.155      347133.153
     1900388.477      347478.589
#Sta/Elev= 30
       0 1738.59    19.8 1733.49    39.6 1729.31    98.9 1719.89   148.4 1710.41
   158.3 1709.36   286.9 1708.99   316.6 1707.37   356.2 1704.07   474.9 1687.28
   484.8 1684.74   522.1 1672.36   534.2 1668.71   544.1 1669.05   547.1 1670.11
     554 1672.55   593.5 1690.15   623.1 1705.11     633 1708.48   642.8 1709.32
   652.7 1707.62   662.6 1703.95     702 1684.79   711.9 1681.84   721.7 1681.37
   800.6 1688.08   830.2 1692.26   909.1  1704.9   928.8 1707.14   948.6 1708.59
#Mann= 3 , 0 , 0
       0      .1       0   522.1    .045       0   547.1      .1       0
Bank Sta=522.1,547.1
XS Rating Curve= 0 ,0
Exp/Cntr=0.3,0.1

Type RM Length L Ch R = 1 ,5652.4  ,305.3,300.8,296.2
XS GIS Cut Line= 3
     1899655.973      346978.071     1899866.749       347335.65
     1900555.239      347604.852
#Sta/Elev= 30
       0  1784.4    39.5    1782    69.2 1778.98   108.7 1772.42   138.4 1765.63
   158.1 1758.94   187.8 1746.93     257 1716.23   276.7 1710.04   296.5 1705.61
   306.4 1704.29   345.9 1703.69   365.7  1702.3   385.4 1698.94   415.1 1691.74
     445 1683.52     465 1679.72   574.9 1666.57   604.9 1661.62   611.1  1661.5
   624.9 1661.35   636.1 1661.41   694.8 1662.18   714.8 1663.58   774.7 1677.34
   804.7  1682.9   914.6 1697.39   954.5  1703.5  1064.4 1724.17  1154.3 1739.76
#Mann= 3 , 0 , 0
       0      .1       0   611.1    .045       0   636.1      .1       0
Bank Sta=611.1,636.1
XS Rating Curve= 0 ,0
Exp/Cntr=0.3,0.1

Type RM Length L Ch R = 1 ,5351.6  ,207.6,209.5,211.3
XS GIS Cut Line= 3
      1899604.09      347092.223     1899831.014       347664.41
     1900476.932      347798.836
#Sta/Elev= 30
       0 1771.13    19.9 1772.18    39.7 1769.02   109.2 1748.91   129.1 1738.25
   168.8 1713.73   188.6 1704.98   198.6  1704.3   208.5 1706.54   228.4 1715.06
   238.3 1717.45   268.1 1718.87   307.8  1718.5   347.5 1714.72   476.6 1707.96
   516.3 1702.88   575.8  1690.6   615.5 1684.83   685.5 1667.99   745.5 1658.04
   747.6 1658.04   772.6 1659.58   815.5 1663.66   825.5 1665.76   865.4 1679.68
   885.4 1682.84   925.4 1682.12   965.4 1685.78  1205.3 1694.21  1275.3 1703.74
#Mann= 3 , 0 , 0
       0      .1       0   747.6    .045       0   772.6      .1       0
Bank Sta=747.6,772.6
XS Rating Curve= 0 ,0
Exp/Cntr=0.3,0.1

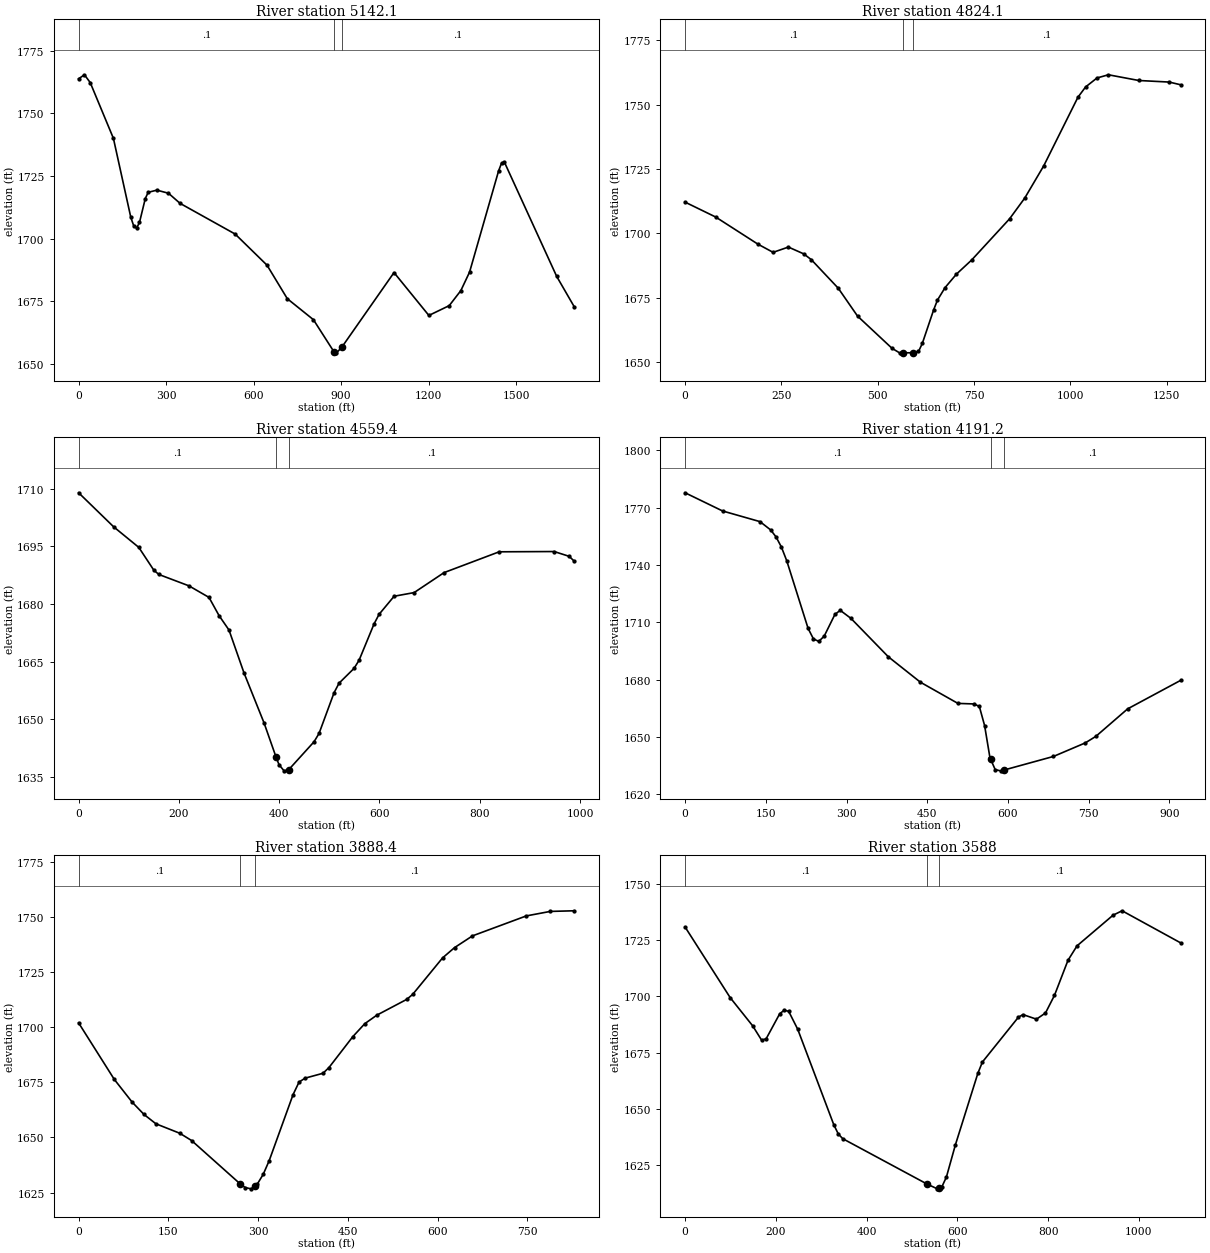
Type RM Length L Ch R = 1 ,5142.1  ,264.1,317.9,371.6
XS GIS Cut Line= 4
     1899581.698      347091.244     1899873.896      347883.583
     1900101.592      347947.766     1899918.961      348537.795
#Sta/Elev= 30
       0 1763.81    19.9 1765.41    39.7  1762.3   119.2 1740.02   178.8 1708.49
   188.8 1705.03   198.7 1704.15   208.6 1706.41   228.5 1715.96   238.4 1718.45
   268.2 1719.32     308 1718.08   347.7 1714.04   536.5 1701.78   645.8 1689.34
   715.3 1675.95   804.8 1667.57   876.5 1654.51   883.9 1654.32   901.5 1656.46
  1081.1 1686.39  1200.6 1669.26  1270.4 1673.18  1310.2 1679.18  1340.1 1686.57
  1439.7 1727.03  1449.7  1730.1  1459.6 1730.48  1638.9 1684.83  1698.7 1672.77
#Mann= 3 , 0 , 0
       0      .1       0   876.5    .045       0   901.5      .1       0
Bank Sta=876.5,901.5
XS Rating Curve= 0 ,0
Exp/Cntr=0.3,0.1

Type RM Length L Ch R = 1 ,4824.1  ,260.9,264.7,268.5
XS GIS Cut Line= 5
     1899640.429      347399.973     1899740.486      347712.056
     1899689.842      347874.101     1899429.553       348208.23
     1899337.676      348561.618
#Sta/Elev= 30
       0 1712.16    79.4 1706.38   188.7 1695.88   228.4 1692.67   268.1 1694.72
   307.9 1692.08   327.7 1689.82   397.6 1678.73   447.6 1667.92   536.9 1655.44
   556.6 1653.66     566 1653.68     591 1653.68   605.8 1654.18   615.7 1657.31
   645.2 1670.38   655.1 1674.16   674.8 1678.99   704.4 1684.23   743.8  1689.7
   842.2 1705.68   881.6 1713.74   930.9 1726.26  1019.7  1752.9  1039.5 1756.87
  1069.1 1760.36  1098.7  1761.6  1177.6 1759.38  1256.6 1758.77  1286.2 1757.72
#Mann= 3 , 0 , 0
       0      .1       0     566    .045       0     591      .1       0
Bank Sta=566,591
XS Rating Curve= 0 ,0
Exp/Cntr=0.3,0.1

Type RM Length L Ch R = 1 ,4559.4  ,392.3,368.4,344.5
XS GIS Cut Line= 3
     1899564.194      347347.562     1899626.135      347600.087
     1899112.864      348116.805
#Sta/Elev= 30
       0 1708.96      70 1700.08     120 1694.74     150  1688.8     160 1687.69
     220 1684.73     260 1681.72     280 1676.99   299.9 1673.22   329.8 1662.06
   369.8 1649.04     394 1640.04   399.7 1638.15   409.7 1636.56     419 1636.86
   469.5 1644.13   479.5  1646.3   509.4 1656.89   519.4 1659.39   549.3 1663.24
   559.3 1665.35   589.2 1674.82   599.2 1677.31   629.2 1682.02   669.1 1682.97
   728.9 1688.18   838.7 1693.59   948.4 1693.66   978.4 1692.41   988.3 1691.16
#Mann= 3 , 0 , 0
       0      .1       0     394    .045       0     419      .1       0
Bank Sta=394,419
XS Rating Curve= 0 ,0
Exp/Cntr=0.3,0.1

Type RM Length L Ch R = 1 ,4191.2  ,282.9,302.5,320.5
XS GIS Cut Line= 3
     1899263.268      346987.345     1899197.942      347530.197
     1899233.052      347902.642
#Sta/Elev= 30
       0 1777.72    69.6 1768.21   139.2 1762.63   159.1 1758.27     169 1754.64
   178.9 1749.39   188.9 1742.17   228.6 1706.78   238.6 1701.25   248.5 1700.02
   258.5 1702.75   278.4  1714.1   288.3 1716.25   308.2 1712.04   377.8 1691.92
   437.4 1678.64     507 1667.58   536.8 1667.29   546.8    1666   556.6 1655.97
   566.5 1639.21   567.9 1638.31   576.3 1632.94   586.2 1632.31   592.9 1632.75
   684.6 1639.84   743.7 1646.92   763.4 1650.35   822.4 1664.72   920.9 1679.62
#Mann= 3 , 0 , 0
       0      .1       0   567.9    .045       0   592.9      .1       0
Bank Sta=567.9,592.9
XS Rating Curve= 0 ,0
Exp/Cntr=0.3,0.1

Type RM Length L Ch R = 1 ,3888.4  ,310.4,300.4,291.9
XS GIS Cut Line= 3
     1899140.142      347309.445     1898928.115      347457.148
     1898627.645      347941.006
#Sta/Elev= 30
       0 1701.95    59.6 1676.33    89.4 1666.03   109.3 1660.42   129.2 1656.19
     169 1651.91   188.8  1648.6   269.7    1629   278.4 1627.27   288.4  1626.7
   294.7 1628.02   298.4  1628.8   308.4 1633.26   318.4 1639.48   358.3 1669.43
   368.3 1675.12   378.3 1676.89   408.3 1679.11   418.3 1681.71   458.2 1695.74
   478.2 1701.62   498.2 1705.46   548.2 1712.62   558.2  1714.9   608.1 1731.44
   628.1  1736.1   658.1 1741.43     748 1750.48     788 1752.52     828 1752.81
#Mann= 3 , 0 , 0
       0      .1       0   269.7    .045       0   294.7      .1       0
Bank Sta=269.7,294.7
XS Rating Curve= 0 ,0
Exp/Cntr=0.3,0.1

Type RM Length L Ch R = 1 ,3588    ,300.5,300,296.2
XS GIS Cut Line= 3
     1898773.695      346834.615     1898639.694      347363.916
     1898505.694      347893.217
#Sta/Elev= 30
       0  1730.9    99.3 1699.48   148.9 1686.91   168.8 1680.47   178.7 1681.18
   208.5 1692.29   218.4 1693.88   228.3 1693.36   248.2 1685.38   327.6 1642.91
   337.5 1638.79   347.4 1636.66   533.5 1616.43   555.9 1614.33   558.5 1614.56
   565.8 1615.22   575.8 1619.56   595.6 1633.89   645.3 1665.86   655.2 1670.81
   734.6 1690.78   744.6 1691.92   774.3 1689.87   794.2 1692.64     814 1700.49
   843.8 1716.11   863.7 1722.53   943.1 1736.18     963 1738.14    1092 1723.85
#Mann= 3 , 0 , 0
       0      .1       0   533.5    .045       0   558.5      .1       0
Bank Sta=533.5,558.5
XS Rating Curve= 0 ,0
Exp/Cntr=0.3,0.1

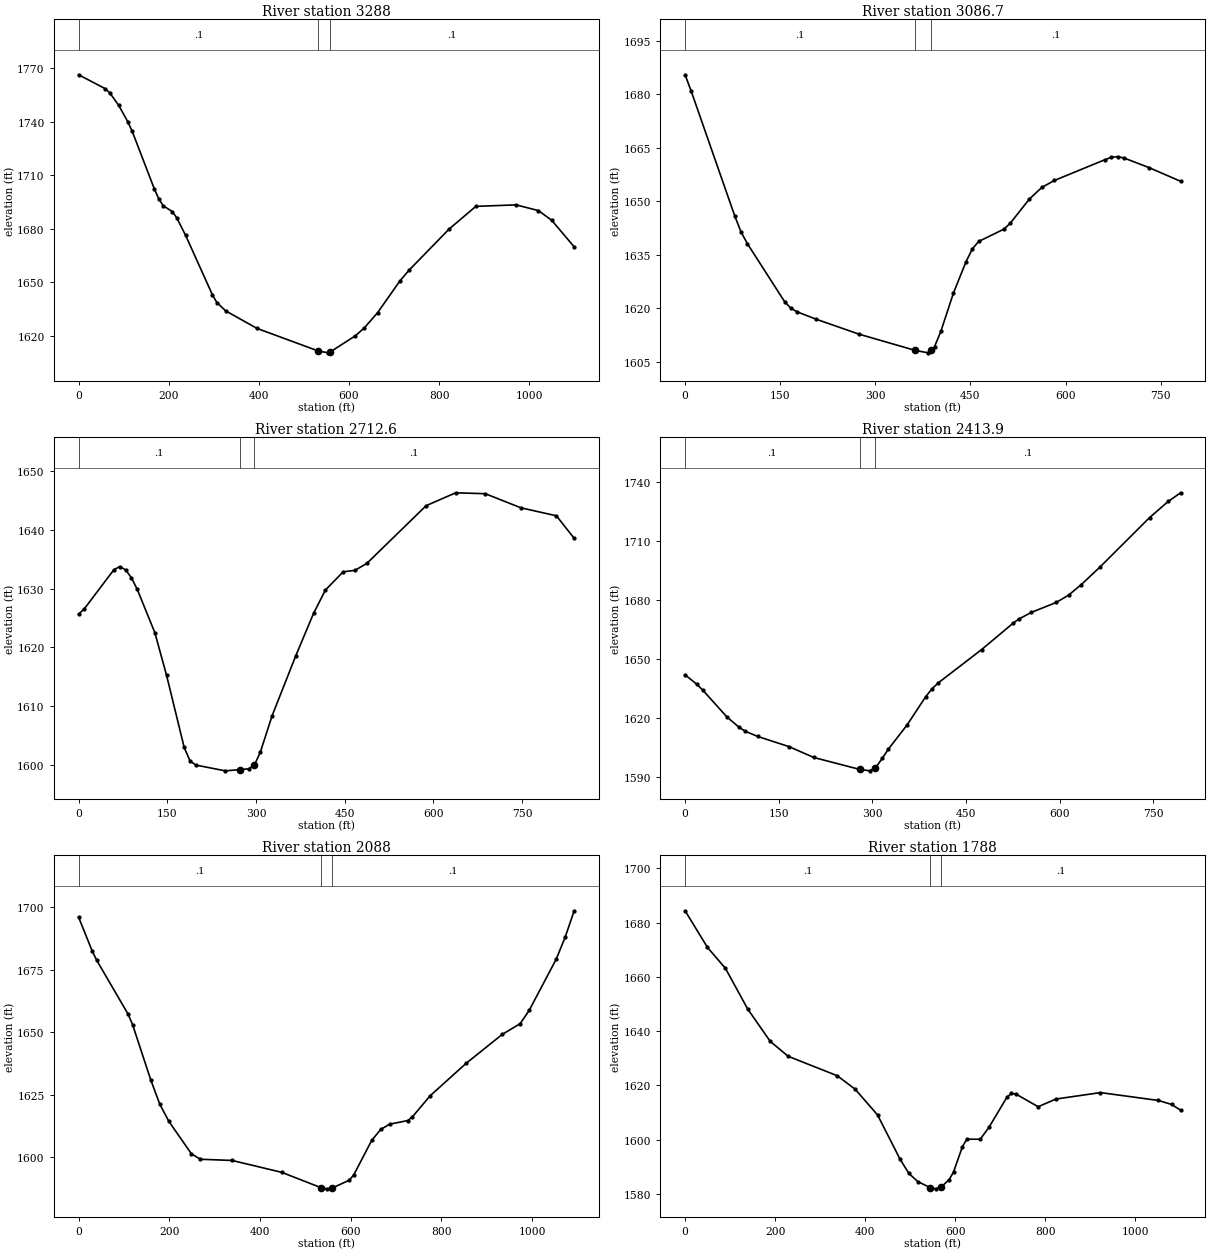
Type RM Length L Ch R = 1 ,3288    ,201.4,201.4,204.8
XS GIS Cut Line= 3
     1898474.999       346755.14     1898350.322      347285.021
     1898289.566      347837.032
#Sta/Elev= 30
       0 1766.29    59.4 1758.45    69.3 1756.08    89.1 1749.07   108.9 1740.04
   118.8 1734.62   168.2 1702.15   178.2  1696.5     188 1692.76   207.8 1689.58
   217.7 1686.09   237.5 1676.18   296.9 1642.87   306.8  1638.5   326.6 1633.83
   395.9 1624.03   531.9 1611.36   554.3 1610.33   556.9 1610.61   613.8 1619.83
   633.6 1624.21   663.4 1632.83   712.9 1650.64   732.8 1656.56     822 1679.72
   881.5 1692.49   970.8 1693.32  1020.4 1690.12  1050.1 1684.61  1099.7 1669.79
#Mann= 3 , 0 , 0
       0      .1       0   531.9    .045       0   556.9      .1       0
Bank Sta=531.9,556.9
XS Rating Curve= 0 ,0
Exp/Cntr=0.3,0.1

Type RM Length L Ch R = 1 ,3086.7  ,410.3,374,337.7
XS GIS Cut Line= 3
     1898265.831      346897.303     1898161.009      347214.152
     1898058.569      347650.116
#Sta/Elev= 30
       0 1685.46     9.8 1680.78    78.5 1645.78    88.3 1641.35    98.2  1638.1
     157 1621.81   166.9 1619.98   176.7 1618.97   206.1 1616.94   274.8 1612.68
   363.3 1608.14   383.5 1607.47   388.3 1608.29   393.4 1609.17   403.4  1613.5
   423.3 1624.26   443.2 1633.08   453.2 1636.66   463.1 1638.72   502.9 1642.17
   512.9 1643.83   542.7 1650.54   562.6 1653.86   582.5 1655.82   662.2 1661.64
   672.1  1662.3   682.1  1662.5     692 1662.14   731.8 1659.42   781.6 1655.58
#Mann= 3 , 0 , 0
       0      .1       0   363.3    .045       0   388.3      .1       0
Bank Sta=363.3,388.3
XS Rating Curve= 0 ,0
Exp/Cntr=0.3,0.1

Type RM Length L Ch R = 1 ,2712.6  ,269.4,298.6,327.9
XS GIS Cut Line= 3
     1897596.399      347268.945      1897884.66      347423.796
     1898124.676      347874.727
#Sta/Elev= 30
       0 1625.66     9.9 1626.61    59.5 1633.22    69.4 1633.76    79.3 1633.22
    89.2 1631.88    99.2 1629.87   128.9 1622.51   148.7 1615.25   178.5 1602.96
   188.4 1600.66   198.3 1599.96   247.9 1598.98   272.2 1599.18   287.6 1599.33
   297.2 1599.94   307.4 1602.21   327.2 1608.37   367.3  1618.6   397.3  1625.8
   417.4 1629.79   447.4 1632.88   467.4 1633.13   487.5 1634.32   587.6 1644.14
   637.7 1646.34   687.8 1646.18   747.9 1643.78     808 1642.42     838 1638.58
#Mann= 3 , 0 , 0
       0      .1       0   272.2    .045       0   297.2      .1       0
Bank Sta=272.2,297.2
XS Rating Curve= 0 ,0
Exp/Cntr=0.3,0.1

Type RM Length L Ch R = 1 ,2413.9  ,326.7,325.9,325.6
XS GIS Cut Line= 3
     1897565.429       347202.24     1897565.429      347268.945
     1897582.105      347995.552
#Sta/Elev= 30
       0 1642.08    19.1 1637.19    28.6  1634.2    66.7 1620.75    86.6 1615.34
    96.6 1613.34   116.5 1610.71   166.3 1605.57   206.1 1600.03   279.3 1593.99
   295.7 1593.24   304.3 1594.85   305.6 1595.09   315.6 1599.52   325.6 1604.33
   355.4 1616.56   385.3 1630.96   395.3 1634.95   405.2 1637.94   474.9 1654.96
   524.7  1668.2   534.6 1670.51   554.6 1673.86   594.4 1678.92   614.3 1682.68
   634.2 1687.94   664.1 1696.84   743.7 1722.06   773.6  1730.3   793.5  1734.7
#Mann= 3 , 0 , 0
       0      .1       0   279.3    .045       0   304.3      .1       0
Bank Sta=279.3,304.3
XS Rating Curve= 0 ,0
Exp/Cntr=0.3,0.1

Type RM Length L Ch R = 1 ,2088    ,290.9,300,307.2
XS GIS Cut Line= 3
      1897220.14      347001.112     1897249.483      347547.324
     1897267.334      348092.615
#Sta/Elev= 30
       0 1695.96    29.8 1682.52    39.8 1678.78   109.4 1657.08   119.4 1652.75
   159.1 1630.82     179 1621.12   198.9 1614.28   248.6 1601.29   268.5 1599.09
   338.2 1598.62   447.6 1593.87   534.5 1587.71     547 1587.25   559.5  1587.6
   596.6  1590.7   606.5 1592.79   646.2 1606.64     666 1611.02   685.9 1613.15
   725.6 1614.58   735.5 1615.99   775.2 1624.54   854.5 1637.52   933.9 1649.07
   973.6  1653.4   993.4 1658.71  1052.9 1679.17  1072.7 1687.99  1092.6 1698.58
#Mann= 3 , 0 , 0
       0      .1       0   534.5    .045       0   559.5      .1       0
Bank Sta=534.5,559.5
XS Rating Curve= 0 ,0
Exp/Cntr=0.3,0.1

Type RM Length L Ch R = 1 ,1788    ,297.5,300,303
XS GIS Cut Line= 3
      1897102.16      346994.341     1896951.116      347530.092
     1896827.569      348059.953
#Sta/Elev= 30
       0  1684.4    49.7 1670.89    89.5  1663.2   139.2 1648.13   188.9  1636.3
   228.6 1630.77     338 1623.57   377.7 1618.61   427.4 1609.14   477.1 1592.92
     497 1587.57   516.9 1584.53   544.1 1582.36   556.6 1581.87   569.1 1582.59
   586.3 1585.23   596.2 1588.07     616 1597.42   625.9 1600.18   655.6 1600.16
   675.3 1604.64   714.9 1615.67   724.8 1617.03   734.7 1616.83   784.2 1612.15
   823.7 1614.98   922.6 1617.36  1051.2 1614.46  1080.9 1612.97  1100.7 1610.86
#Mann= 3 , 0 , 0
       0      .1       0   544.1    .045       0   569.1      .1       0
Bank Sta=544.1,569.1
XS Rating Curve= 0 ,0
Exp/Cntr=0.3,0.1