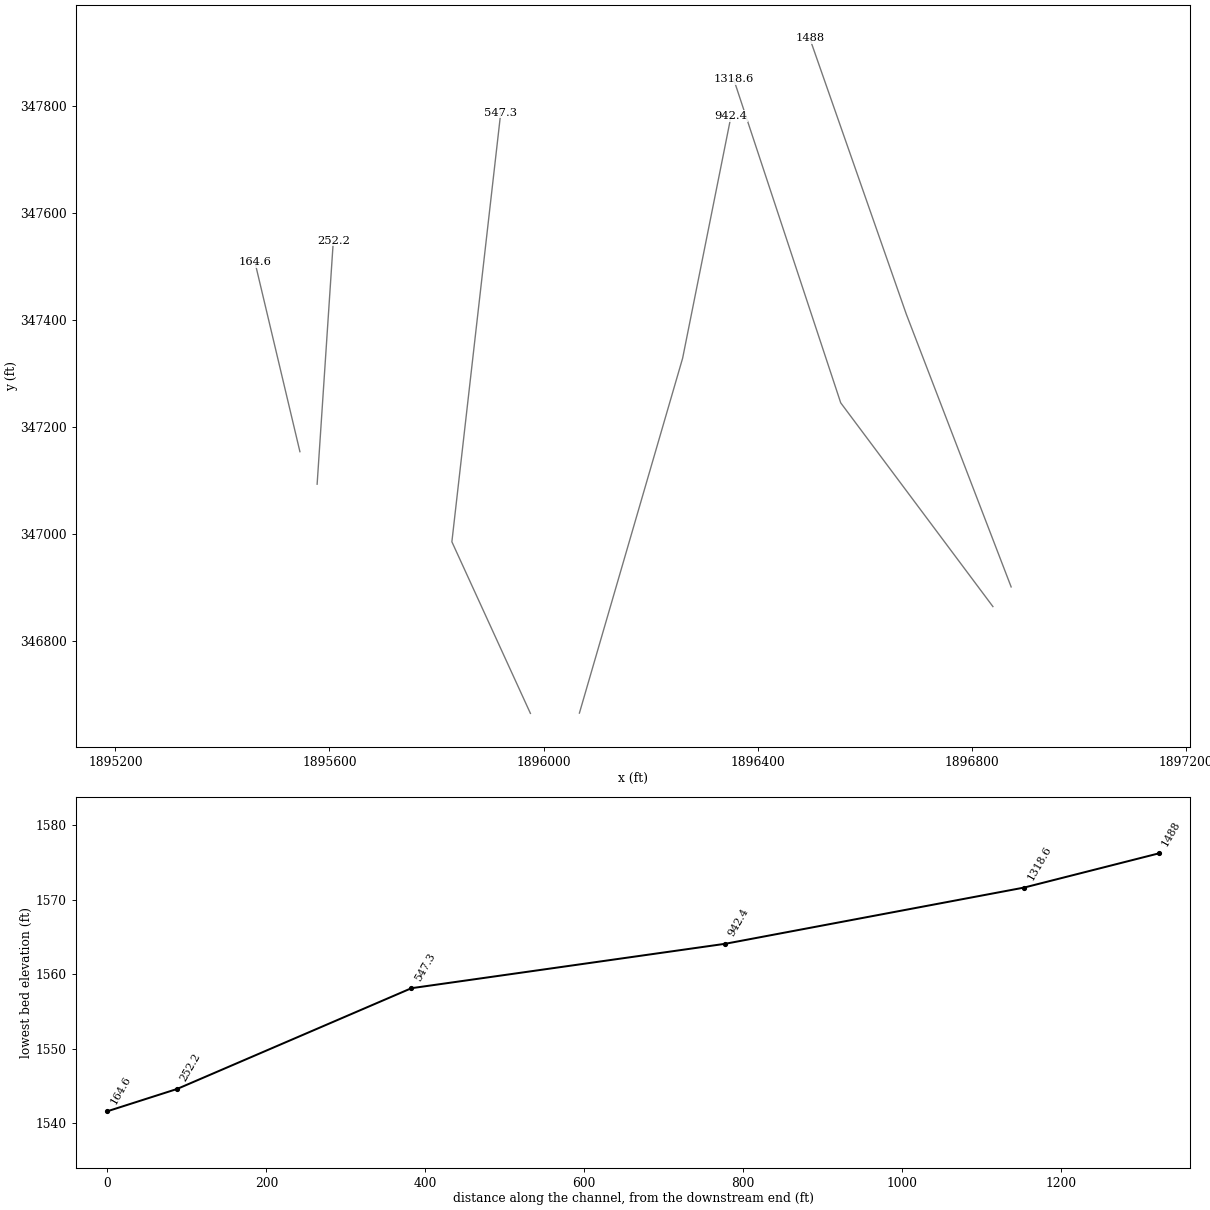
HEC-RAS study PlmOrchdCk.prj: PlmOrchdCk

--- PlmOrchdCk.g01 (geometry) --- (continued)

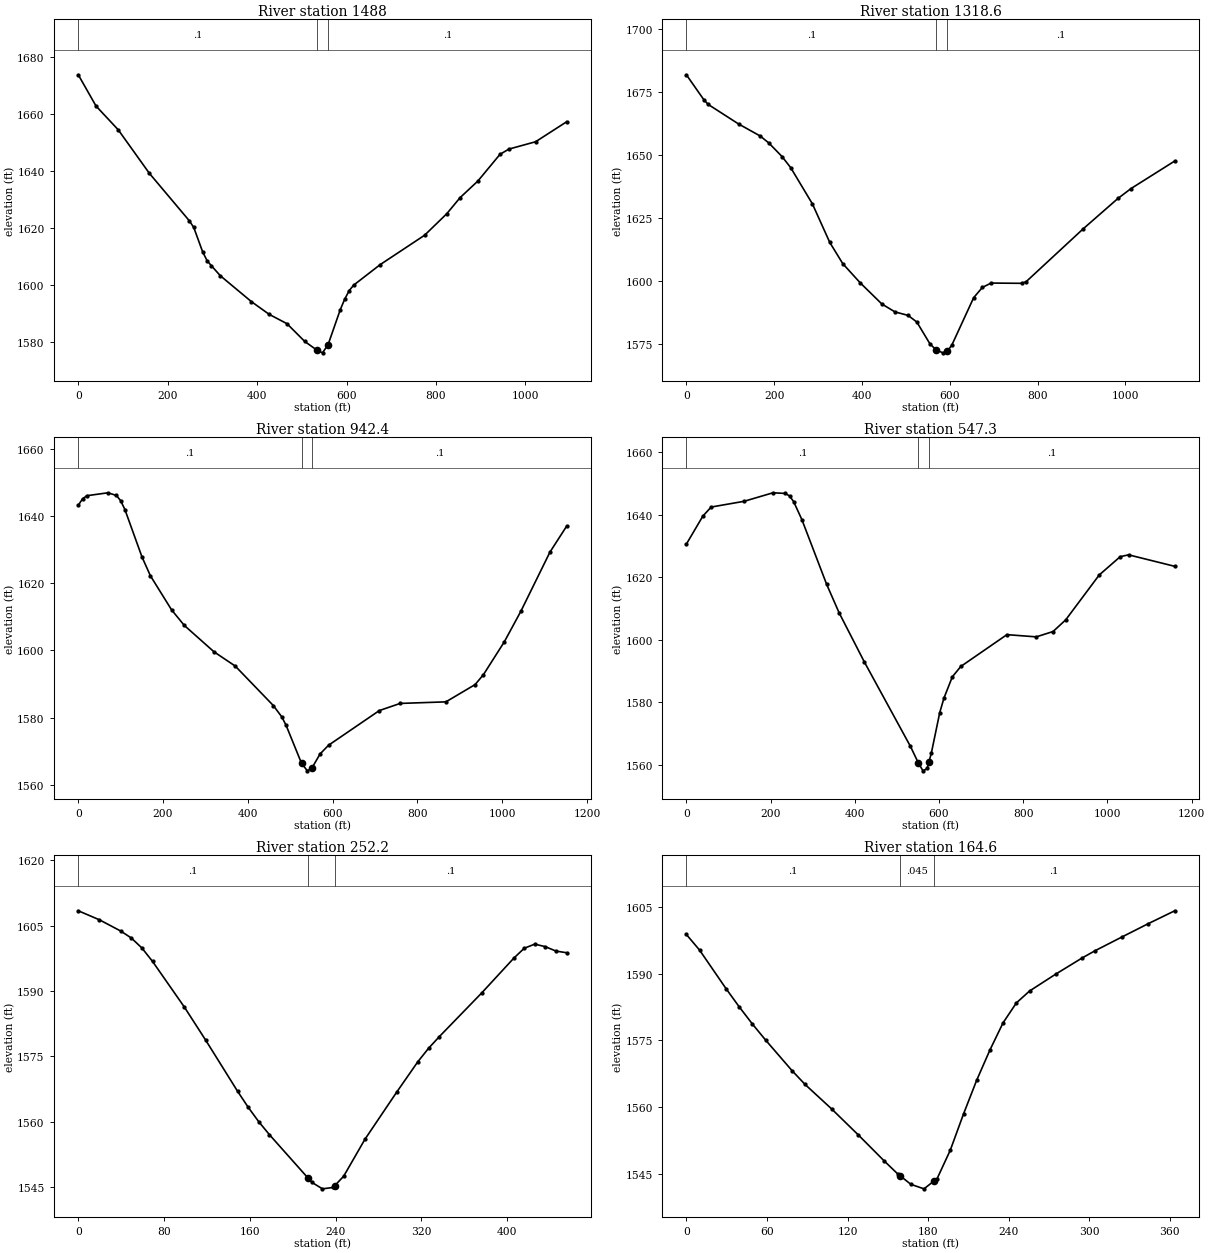
Type RM Length L Ch R = 1 ,1488    ,170.8,169.4,168.8
XS GIS Cut Line= 3
     1896873.807      346901.119     1896677.839      347410.928
     1896497.478      347926.245
#Sta/Elev= 30
       0 1673.69    39.7 1662.74    89.4  1654.4   158.9 1639.17   248.3 1622.53
   258.2  1620.2     278 1611.69     288 1608.55   297.9 1606.73   317.8 1603.24
   387.3 1594.17     427 1589.72   466.7 1586.46   506.4 1580.24   533.7 1577.18
   546.2 1576.24   558.7 1579.13   585.9 1591.37   595.8 1595.04   605.7 1598.01
   615.7 1599.95   675.2 1607.16   774.5 1617.46   824.1    1625   853.9 1630.64
   893.6 1636.45   943.2 1645.83   963.1 1647.65  1022.7 1650.22  1092.1 1657.22
#Mann= 3 , 0 , 0
       0      .1       0   533.7    .045       0   558.7      .1       0
Bank Sta=533.7,558.7
XS Rating Curve= 0 ,0
Exp/Cntr=0.3,0.1

Type RM Length L Ch R = 1 ,1318.6  ,392.6,376,359.4
XS GIS Cut Line= 3
     1896839.735      346864.382     1896555.326      347245.122
     1896355.211      347850.231
#Sta/Elev= 30
       0 1681.72    39.6 1671.88    49.5    1670   118.8 1662.26   168.3 1657.47
   188.1 1654.68   217.8 1649.37   237.6 1644.98   287.1 1630.62   326.7 1615.35
   356.4 1606.93     396 1599.37   445.5 1590.96   475.2 1587.86   505.1 1586.47
     525 1583.85   554.9 1575.21   569.7  1572.7   584.8 1571.65   594.7 1572.36
   604.7 1574.69   654.5 1593.48   674.4 1597.56   694.3 1599.27     764 1599.17
     774 1599.81   903.4 1620.64   983.1 1632.75    1013 1636.68  1112.6 1647.58
#Mann= 3 , 0 , 0
       0      .1       0   569.7    .045       0   594.7      .1       0
Bank Sta=569.7,594.7
XS Rating Curve= 0 ,0
Exp/Cntr=0.3,0.1

Type RM Length L Ch R = 1 ,942.4   ,390.4,395.1,399.8
XS GIS Cut Line= 3
     1896067.028      346665.364     1896259.918      347328.503
     1896350.446      347781.144
#Sta/Elev= 30
       0 1643.32      10 1645.23      20 1646.17    70.1 1647.05    90.1 1646.24
   100.1 1644.67   110.1 1642.02   150.1 1627.98   170.2 1622.28   220.2 1612.11
   250.2 1607.48   320.3  1599.6   370.3 1595.36   460.4 1583.55   480.4 1580.15
   490.4 1577.66   526.7 1566.36   540.5  1564.1   551.7 1565.03   570.5 1569.14
   590.5 1571.74   710.3 1582.08   759.4 1584.21   867.4 1584.68   936.2 1589.83
   955.8 1592.77  1004.9 1602.53  1044.2  1611.7  1112.9 1629.37  1152.2 1637.08
#Mann= 3 , 0 , 0
       0      .1       0   526.7    .045       0   551.7      .1       0
Bank Sta=526.7,551.7
XS Rating Curve= 0 ,0
Exp/Cntr=0.3,0.1

Type RM Length L Ch R = 1 ,547.3   ,293.7,295,296.3
XS GIS Cut Line= 3
     1895975.476      346664.822     1895828.719      346985.449
     1895920.068      347787.381
#Sta/Elev= 30
       0 1630.55    39.2  1639.5    58.8 1642.38   137.1 1644.22   205.7 1646.94
   235.1 1646.73   244.9 1645.93   254.7 1644.12   274.3 1638.36     333 1617.73
   362.6 1608.63   422.4 1592.96     532 1565.96   550.9 1560.64   561.9 1558.13
   571.8 1558.88   575.9 1560.92   581.8 1563.86   601.7 1576.75   611.7 1581.38
   631.6 1588.17   651.6 1591.46   761.2 1601.63   830.9 1600.92   870.8 1602.63
   900.7 1606.34   980.4 1620.69  1030.2 1626.53  1050.1 1627.12  1159.7 1623.45
#Mann= 3 , 0 , 0
       0      .1       0   550.9    .045       0   575.9      .1       0
Bank Sta=550.9,575.9
XS Rating Curve= 0 ,0
Exp/Cntr=0.3,0.1

Type RM Length L Ch R = 1 ,252.2   ,79.3,87.6,95.8
XS GIS Cut Line= 2
     1895576.921        347093.1     1895607.163      347547.676
#Sta/Elev= 30
       0 1608.41    19.8 1606.33    39.6 1603.76    49.5 1602.16    59.4 1599.86
    69.3 1596.78      99  1586.3   118.8 1578.74   148.6 1566.99   158.5 1563.32
   168.4 1559.99   178.3 1557.03   214.4 1547.05   217.9 1546.08   227.8 1544.59
   237.7 1544.91   239.4 1545.35   247.6 1547.49   267.4 1555.95   297.1  1566.8
   316.9  1573.8   326.8 1576.85   336.7 1579.49   376.4 1589.56   406.1 1597.48
     416  1599.8   425.9 1600.76   435.8 1600.16   445.7 1599.16   455.6 1598.78
#Mann= 3 , 0 , 0
       0      .1       0   214.4    .045       0   239.4      .1       0
Bank Sta=214.4,239.4
XS Rating Curve= 0 ,0
Exp/Cntr=0.3,0.1

Type RM Length L Ch R = 1 ,164.6   ,158.7,164.6,170.5
XS GIS Cut Line= 2
      1895544.76      347153.849     1895460.783      347507.624
#Sta/Elev= 30
       0 1598.78     9.8 1595.28    29.5 1586.62    39.3 1582.53    49.1 1578.67
      59 1575.04    78.6 1568.19    88.4 1565.06   108.1 1559.58   127.8 1553.78
   147.4 1547.84   157.2    1545   159.1 1544.54   167.1 1542.62   176.9  1541.6
   184.1  1543.3   186.7 1543.91   196.5  1550.3   206.4 1558.48   216.2 1566.06
     226 1572.81   235.8 1578.93   245.7  1583.4   255.5 1586.07   275.2 1589.91
   294.8 1593.53   304.6 1595.18   324.3 1598.22     344 1601.23   363.6 1604.11
#Mann= 3 , 0 , 0
       0      .1       0   159.1    .045       0   184.1      .1       0
Bank Sta=159.1,184.1
XS Rating Curve= 0 ,0
Exp/Cntr=0.3,0.1

Chan Stop Cuts=-1
Use User Specified Reach Order=0
Composite Channel Slope=5